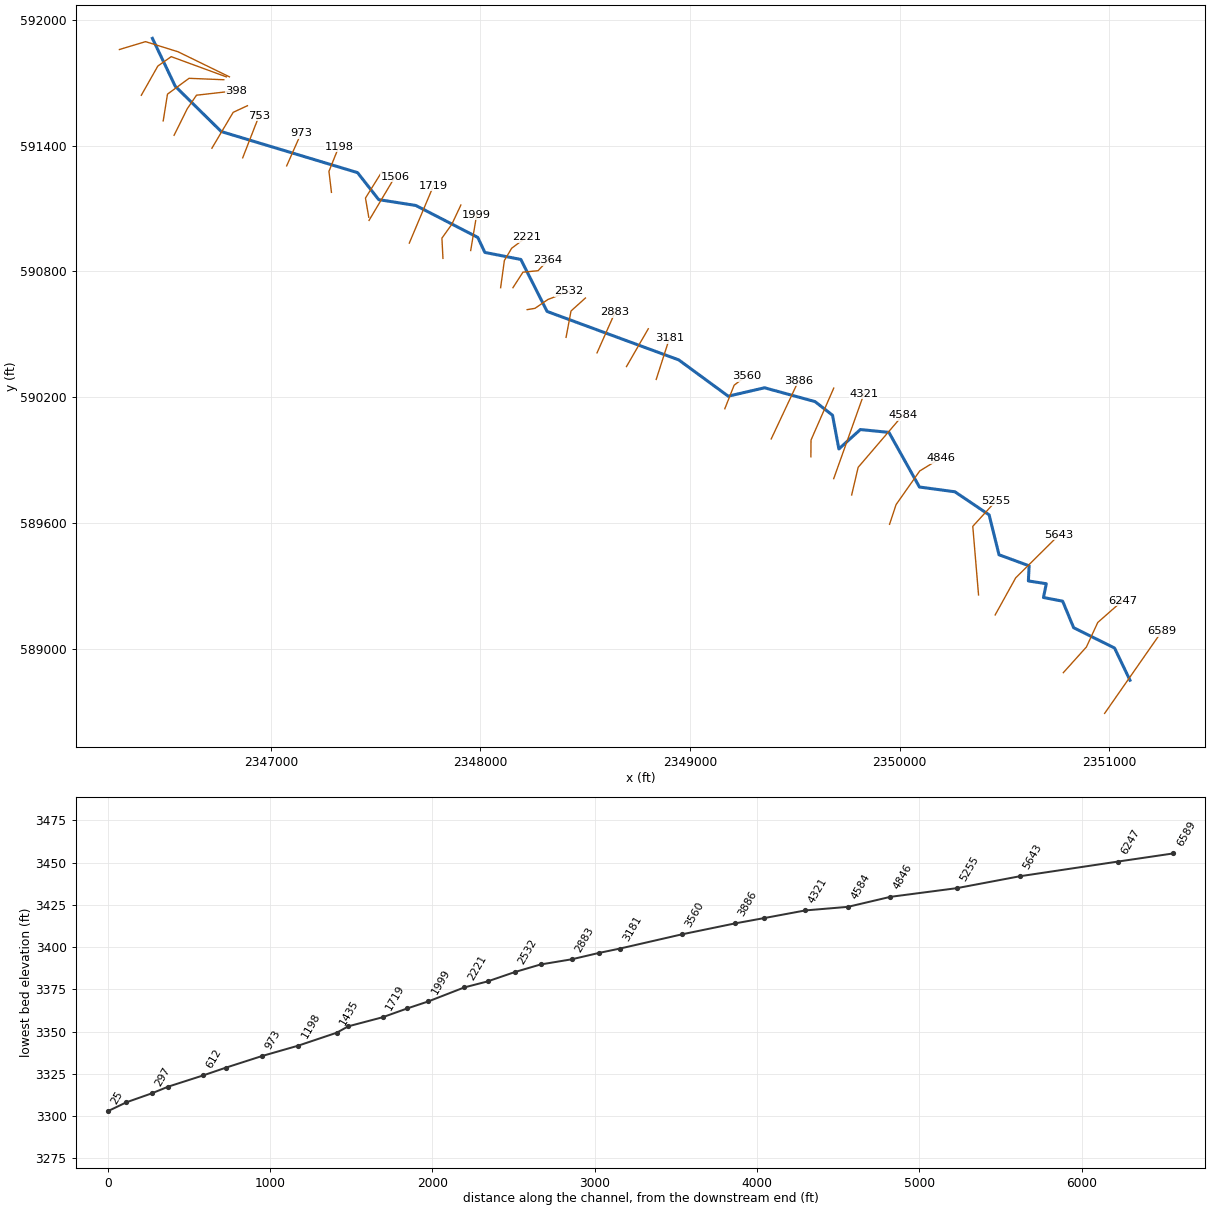
--- ABESRN.prj (project) ---

Proj Title=ABESRN
Current Plan=p01
Default Exp/Contr=0,0
English Units
Geom File=g01
Flow File=f01
Plan File=p01
Background Map Layer=Inundation Boundary (01pct Value_0)
BEGIN DESCRIPTION:
----------MODEL BY WOOD PLC 2021----------
Stream Name: Abes Run
Flood Zone: Enhanced Approximate
Pocahontas County, WV
HEC-RAS Version: RAS 6.1
Vertical Datum: NAVD88
Projection: NAD 1983 StatePlane West Virginia S FIPS 4702 (US Feet)
Terrain: 1-meter LIDAR (FEMA Region III 3DEP collected 2016-2018)
Land Use: 2019 NLCD
Hydrologic Method:
WV SIR2010-5033 regression equations
Model Notes:
Normal depth tie in to East fork Greenbrier River
END DESCRIPTION:
DSS Export Rating Curves= 0
DSS Export Rating Curve Sorted= 0
DSS Export Volume Flow Curves= 0
DXF OffsetX= 0
DXF OffsetY= 0
DXF ScaleX= 0
DXF ScaleY= 0

--- ABESRN.p01 (plan) ---

Plan Title=Floodplain
Program Version=6.10
Short Identifier=Floodplain
Geom File=g01
Flow File=f01
Subcritical Flow
K Sum by GR= 0
Std Step Tol= 0.01
Critical Tol= 0.01
Num of Std Step Trials= 20
Max Error Tol= 0.3
Flow Tol Ratio= 0.001
Split Flow NTrial= 30
Split Flow Tol= 0.02
Split Flow Ratio= 0.02
Log Output Level= 0
Friction Slope Method= 1
Unsteady Friction Slope Method= 2
Unsteady Bridges Friction Slope Method= 1
Parabolic Critical Depth
Global Vel Dist= 0 , 0 , 0
Global Log Level= 0
CheckData=True
Encroach Param=-1 ,0,0, 0
Mapping Interval=1HOUR
Computation Time Step Use Courant=        0
Computation Time Step Use Time Series=    0
Computation Time Step Count To Double=0
Computation Time Step Max Doubling=0
Computation Time Step Max Halving=0
Computation Time Step Residence Courant=0
Run HTab= 0
Run UNet= 0
Run Sediment= 0
Run PostProcess= 0
Run WQNet= 0
Run RASMapper=-1
UNET Theta= 0
UNET Theta Warmup= 0
UNET ZTol= 0
UNET ZSATol= 0
UNET MxIter= 0
UNET Max Iter WO Improvement= 0
UNET MaxInSteps= 0
UNET DtIC= 0
UNET DtMin= 0
UNET MaxCRTS= 0
UNET WFStab= 0
UNET SFStab= 0
UNET WFX= 1
UNET SFX= 1
UNET Gravity=32.174
UNET 1D Methodology=Finite Difference
UNET DSS MLevel= 1
UNET Pardiso=0
UNET DZMax Abort= 0
UNET Use Existing IB Tables= 0
UNET Froude Reduction=False
UNET Froude Limit= 0
UNET Froude Power= 0
UNET D1 Cores= 0
UNET WindReference=Eulerian
UNET WindDragFormulation=Hsu (1988)
UNET D2 Coriolis=0
UNET D2 Cores= 0
UNET D2 Theta= 1
UNET D2 Theta Warmup= 1
UNET D2 Z Tol= 0.01
UNET D2 Volume Tol= 0.01
UNET D2 Max Iterations= 20
UNET D2 Equation= 0
UNET D2 RampUpFraction=0.1
UNET D2 TimeSlices= 1
UNET D2 Turbulence Formulation=Non-Conservative (original)
UNET D2 Eddy Viscosity=0.3
UNET D2 Transverse Eddy Viscosity=0.1
UNET D2 Smagorinsky Mixing=0
UNET D2 BCVolumeCheck=0
UNET D2 Cores=0
UNET D2 SolverType=PARDISO (Direct)
UNET D2 Minimum Iterations= 2147483647
UNET D2 Maximum Iterations= 2147483647
UNET D2 Restart Number= 10
UNET D2 Relaxation Coeff=1.3
UNET D2 SOR Precondition Iterations= 10
UNET D2 ILUT Maximum Fill= 8
UNET D2 ILUT Tolerance=1E-08
UNET D1D2 MaxIter= 0
UNET D1D2 ZTol=0.01
UNET D1D2 QTol=0.1
UNET D1D2 MinQTol=1
Write IC File= 0
Write IC File at Fixed DateTime=0
Write IC File at Sim End=0
Echo Input=False
Echo Parameters=False
Echo Output=False
Write Detailed= 0
HDF Write Warmup=0
HDF Write Time Slices=0
HDF Flush=0
HDF Compression= 1
HDF Chunk Size= 1
HDF Spatial Parts= 1
HDF Use Max Rows=0
HDF Fixed Rows= 1
Calibration Method= 0
Calibration Iterations= 20
Calibration Max Change=0.05
Calibration Tolerance=0.2
Calibration Maximum=1.5
Calibration Minimum=0.5
Calibration Optimization Method= 1
WQ AD Non Conservative
WQ ULTIMATE=-1
WQ Max Comp Step=1HOUR
WQ Output Interval=15MIN
WQ Output Selected Increments= 0
WQ Output face flow=0
WQ Output face velocity=0
WQ Output face area=0
WQ Output face dispersion=0
WQ Output cell volume=0
WQ Output cell surface area=0
WQ Output cell continuity=0
WQ Output cumulative cell continuity=0
WQ Output face conc=0
WQ Output face dconc_dx=0
WQ Output face courant=0
WQ Output face peclet=0
WQ Output face adv mass=0
WQ Output face disp mass=0
WQ Output cell mass=0
WQ Output cell source sink temp=0
WQ Output nsm pathways=0
WQ Output nsm derived pathways=0
WQ Create Restart=0
WQ Fixed Restart=0
WQ System Summary=0
WQ Write To DSS=0
Sorting and Armoring Iterations= 10
XS Update Threshold= 0.02
Bed Roughness Predictor= 0
Hydraulics Update Threshold= 0.02
Energy Slope Method= 1
Volume Change Method= 1
Sediment Retention Method= 0
Sediment TS Multiplier= 1
Warm Up Method= 0
XS Weighting Method= 0
Number of US Weighted Cross Sections= 1
Number of DS Weighted Cross Sections= 1
Upstream XS Weight=0
Main XS Weight=1
Downstream XS Weight=0
Number of DS XS's Weighted with US Boundary= 1
Upstream Boundary Weight= 1
Weight of XSs Associated with US Boundary= 0
Number of US XS's Weighted with DS Boundary= 1
Downstream Boundary Weight= 0.5
Weight of XSs Associated with DS Boundary= 0.5
Percentile Method= 0
Sediment Output Level= 3
Mass or Volume Output= 0
Output Increment Type= 1
Profile and TS Output Increment= 1
Transport Output Increment 1
XS Output Flag= 0
XS Output Increment= 10
Read HDF5 Sediment Hotstart= 0
Sediment Hotstart Type= 0
Write Gradation File= 0
Read Gradation Hotstart= 0
Write HDF5 File= 1
Write Binary Output= 1
Write DSS Sediment File= 0
DSS Sediment Output Type= 1
SV Curve= 0
Specific Gage Flag= 0
Subcell Erosion Methods= 0
Subcell Deposition Methods= 0
Advection Scheme= 1
Matrix Solver= 0
Implicit Weighting Factor= 1
Maximum Outer Loop Convergence Iterations= 5
Convergence Maximum Absolute= 0.001
Convergence RMSE= 0.0001
Grain Fractions Max Abs Error= 0.001
Max Subgrid Regions= 1
Max Subgrid Length Scale= 3.402823E+38
Initial Layer Thickness= 3.402823E+38
Min Layer Thickness= 3.402823E+38
Max Layer Thickness= 3.402823E+38
Number of Layers= 5

--- ABESRN.f01 (steady flow) ---

Flow Title=Flow
Program Version=6.10
Number of Profiles= 6
Profile Names=01pct,10pct,04pct,02pct,0_2pct,01plus
River Rch & RM=ABESRN,Main            ,6589
     589     312     414     499     823     872
River Rch & RM=ABESRN,Main            ,1999
     697     371     492     591     970    1030
Boundary for River Rch & Prof#=ABESRN,Main            , 1
Up Type= 0
Dn Type= 3
Dn Slope=0.0442
Boundary for River Rch & Prof#=ABESRN,Main            , 2
Up Type= 0
Dn Type= 3
Dn Slope=0.0442
Boundary for River Rch & Prof#=ABESRN,Main            , 3
Up Type= 0
Dn Type= 3
Dn Slope=0.0442
Boundary for River Rch & Prof#=ABESRN,Main            , 4
Up Type= 0
Dn Type= 3
Dn Slope=0.0442
Boundary for River Rch & Prof#=ABESRN,Main            , 5
Up Type= 0
Dn Type= 3
Dn Slope=0.0442
Boundary for River Rch & Prof#=ABESRN,Main            , 6
Up Type= 0
Dn Type= 3
Dn Slope=0.0442
DSS Import GetInterval= 0
DSS Import GetPeak= 0
DSS Import FillOption= 0

--- ABESRN.g01 (geometry) ---

Geom Title=Geometry
Program Version=6.10

River Reach=ABESRN          ,Main
Reach XY= 30
     2351098.861       588849.59     2351025.232      589003.332
     2350830.143      589100.2162350777.69910162589226.693800969
     2350686.216      589244.3332350699.59026621589310.009892077
      2350614.15       589323.32     2350617.723      589395.461
     2350474.067      589448.188     2350426.854      589638.602
2350263.71233369589748.644607024     2350094.502      589771.408
2349948.92895233 590032.090132622349812.60480315590045.629174833
2349709.99851727589953.023435978      2349679.75      590113.977
2349596.32267656  590178.93978442349355.45307719590244.852975106
      2349182.15       590204.762348946.24120388590377.823952238
     2348317.994      590609.021     2348192.734      590857.077
2348021.07331932590890.595723413 2347987.3553981 590962.18146385
     2347691.919       591114.58     2347514.654      591142.546
 2347413.6320001591271.348864579     2346763.352      591467.326
      2346543.98      591683.332     2346434.905      591912.029

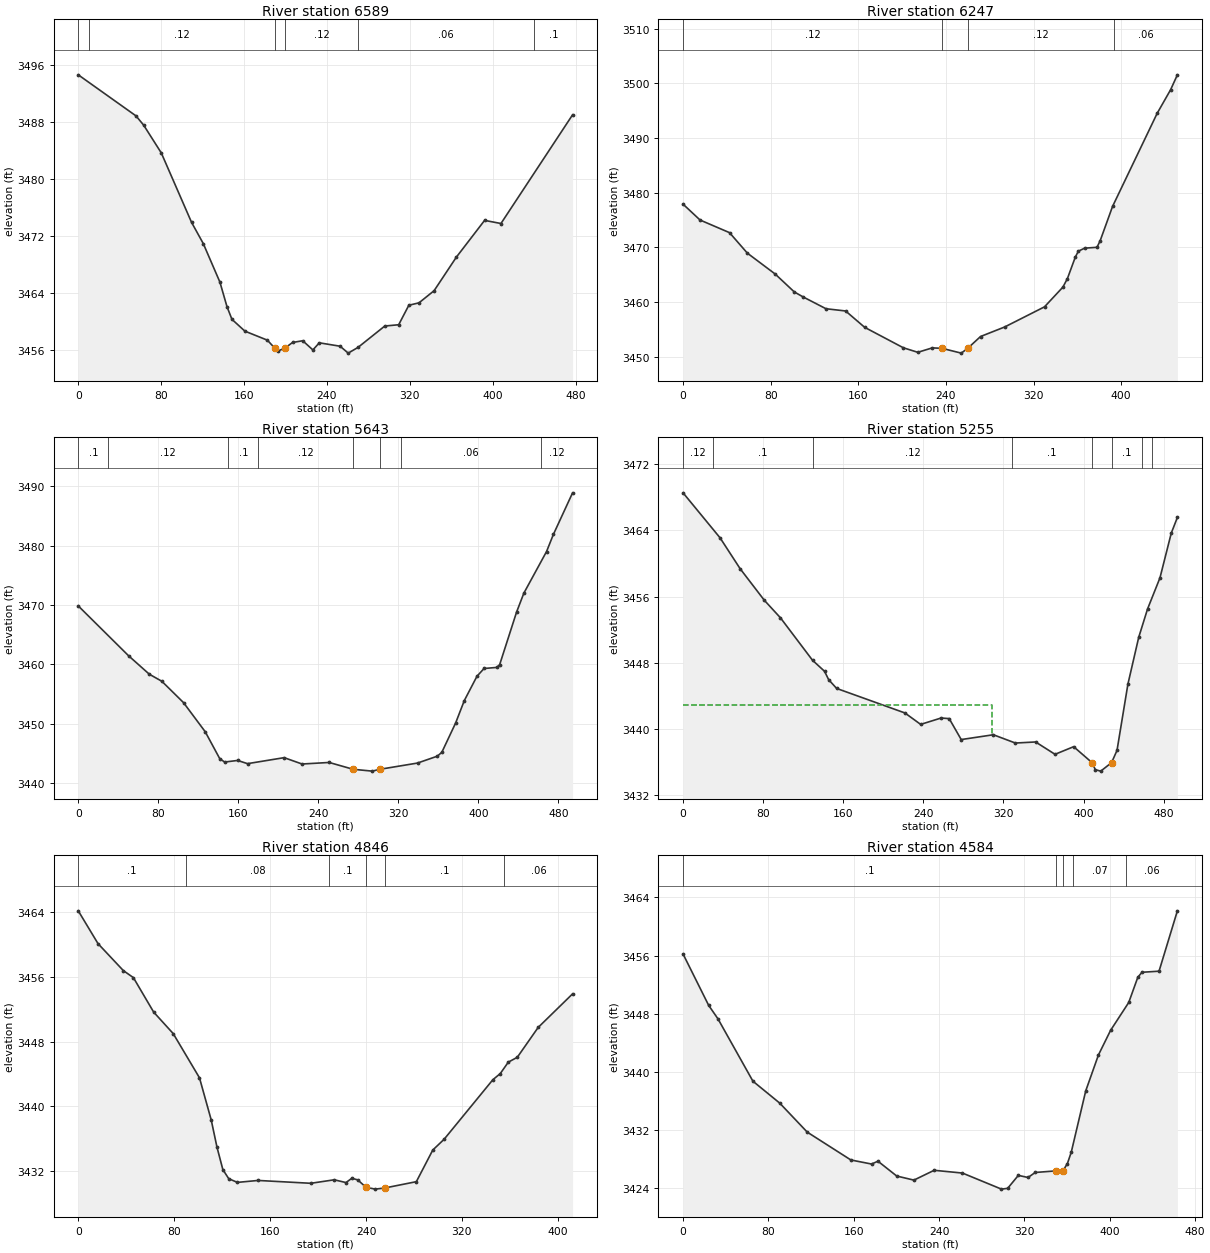
Type RM Length L Ch R = 1 ,6589    ,342.2,342.2,342.2
XS GIS Cut Line= 2
2350978.01251977588691.4865650842351250.78903549 589082.79324367
#Sta/Elev= 30
       0 3494.62    55.7 3488.85    63.1 3487.55    80.1 3483.65   109.3 3473.89
   120.6 3470.91   136.7 3465.48   143.5 3462.04   148.3 3460.25   160.8 3458.59
   182.5 3457.32   189.5 3456.22   192.4 3455.78   199.6 3456.22   206.8    3457
   216.6 3457.24   226.4 3455.95   232.6 3456.95   252.7 3456.47   260.5  3455.5
     270 3456.31   295.8 3459.31   309.2 3459.49     319 3462.23   328.8 3462.57
   343.4 3464.28   364.8 3468.98   392.1 3474.16   407.9 3473.72     477    3489
#Mann= 6 ,-1,0
       0      .1       0      10     .12       0   189.5    .045       0
   199.6     .12       0     270     .06       0     440      .1       0
Bank Sta=189.5,199.6
XS Rating Curve= 0 ,0
Exp/Cntr=0.3,0.1

Type RM Length L Ch R = 1 ,6247    ,583.9,604.2,588.9
XS GIS Cut Line= 4
2350780.95087023588885.6658391262350890.99653212589008.097854256
2350945.22406836589125.2293325312351063.60369103589229.325177309
#Sta/Elev= 30
       0 3477.92    15.5 3475.02    42.4 3472.71    58.7 3468.96    84.1 3465.14
   101.5 3461.87   109.6 3460.95   130.5 3458.79   148.4 3458.38   165.8 3455.39
   201.1 3451.65   214.3 3450.82   227.5 3451.63   236.3 3451.55     254 3450.67
   259.7 3451.52   271.6 3453.71   293.7 3455.46     330 3459.14   346.8 3462.75
   350.9 3464.31   358.1 3468.23   360.9 3469.32   366.6 3469.87   377.9 3470.03
   380.8 3471.23   392.1  3477.5   432.9 3494.56   445.1 3498.85   451.3 3501.58
#Mann= 4 ,-1,0
       0     .12       0   236.3    .045       0   259.7     .12       0
  393.69     .06       0
Bank Sta=236.3,259.7
XS Rating Curve= 0 ,0
Exp/Cntr=0.3,0.1

Type RM Length L Ch R = 1 ,5643    ,378.9,388.1,379.2
XS GIS Cut Line= 3
2350455.69883792589161.1542099572350553.63124516589338.067048067
2350761.00090356589543.458096226
#Sta/Elev= 30
       0 3469.83    50.4 3461.41      71 3458.32    83.6 3457.12   105.2 3453.53
   126.9 3448.62   141.4 3444.09   146.3 3443.51   159.3 3443.78   169.2 3443.24
   205.8 3444.25   223.7 3443.18   250.8 3443.44   274.8 3442.29   293.9 3441.98
   301.5 3442.29   339.1 3443.34   358.9  3444.5   363.4 3445.15   377.2 3450.09
   385.9 3453.88   398.5 3457.96   405.6 3459.28   418.3 3459.46   421.2 3459.92
   438.1 3468.77   445.4 3471.98   468.1    3479   474.9 3481.87   494.1 3488.89
#Mann= 8 ,-1,0
       0      .1       0      30     .12       0     150      .1       0
     180     .12       0   274.8    .045       0   301.5     .12       0
  322.21     .06       0  462.21     .12       0
Bank Sta=274.8,301.5
XS Rating Curve= 0 ,0
Exp/Cntr=0.3,0.1

Type RM Length L Ch R = 1 ,5255    ,402.8,409.2,408.4
XS GIS Cut Line= 3
2350376.43165522589256.3471263332350348.92600907589583.887580563
2350460.31063532589705.664527559
#Sta/Elev= 30
       0 3468.53      37 3463.09      57 3459.37    81.1 3455.57    97.3 3453.44
   129.3 3448.32   141.3 3446.99   145.4 3445.98   153.4 3444.92   221.6 3441.96
   237.3 3440.58   257.7 3441.35   265.8 3441.28   277.8 3438.75   309.9 3439.33
   331.9 3438.33   352.1 3438.46   371.5 3436.97   390.1 3437.89   408.4 3435.97
   411.8 3435.11   417.2 3434.94427.97583435.968   433.4 3437.44   444.3 3445.45
   455.1  3451.1   463.9 3454.51   476.3 3458.27   487.6 3463.67   493.7 3465.56
#Mann= 8 ,-1,0
       0     .12       0      30      .1       0     130     .12       0
  328.69      .1       0   408.4    .045       0427.9758      .1       0
  458.69     .12       0  468.69     .06       0
#XS Ineff= 2 , 0
          308.14 3442.88
Permanent Ineff=
       F       F
Bank Sta=408.4,427.9758
XS Rating Curve= 0 ,0
Exp/Cntr=0.3,0.1

Type RM Length L Ch R = 1 ,4846    ,263.6,261.8,257.7
XS GIS Cut Line= 4
2349951.80482996589593.5033798042349982.98470571589687.518349098
2350095.75090569 589847.993325992350195.61920863589909.214906454
#Sta/Elev= 30
       0 3464.12    16.5 3460.07    37.6 3456.75      46 3455.88    62.9 3451.63
    79.2 3448.98   101.1 3443.53   110.9 3438.33   115.7 3434.98   120.6 3432.21
   125.5 3431.09   132.7 3430.63     150 3430.87     194 3430.52   213.5 3430.95
   223.3 3430.61   228.2 3431.14   233.1 3430.94239.9745 3430.03   247.7  3429.8
255.69993429.942     282 3430.72   295.7 3434.62   305.1 3435.94   345.8 3443.29
     352 3444.05   358.7 3445.46   366.2 3446.06   383.6 3449.74   412.3 3453.88
#Mann= 6 ,-1,0
       0      .1       0      90     .08       0  209.05      .1       0
239.9745    .045       0255.6999      .1       0  355.18     .06       0
Bank Sta=239.9745,255.6999
XS Rating Curve= 0 ,0
Exp/Cntr(USF)=0,0
Exp/Cntr=0.3,0.1

Type RM Length L Ch R = 1 ,4584    ,257,262.5,251
XS GIS Cut Line= 3
2349771.08338487589733.3683424962349802.06311014 589865.34197214
2350015.20361999  590114.4189633
#Sta/Elev= 30
       0 3456.21      24 3449.15    32.7  3447.3    65.5 3438.72    90.6 3435.71
   116.4 3431.72   157.3 3427.89   176.7 3427.33   182.7 3427.72   200.3 3425.68
   216.4 3425.12   235.4 3426.47   261.9 3426.09   298.5 3423.88   304.3 3423.99
   314.3 3425.77   323.4 3425.48   330.1 3426.17   349.7 3426.39  356.27 3426.43
   360.3  3427.4   363.9 3428.95   377.5  3437.4   389.4 3442.33   400.8 3445.72
   417.8 3449.55   426.3 3453.01   430.2  3453.7   446.2 3453.85   463.4 3462.15
#Mann= 5 ,-1,0
       0      .1       0   349.7    .045       0  356.27      .1       0
  365.56     .07       0  415.56     .06       0
Bank Sta=349.7,356.27
XS Rating Curve= 0 ,0
Exp/Cntr(USF)=0,0
Exp/Cntr=0.3,0.1

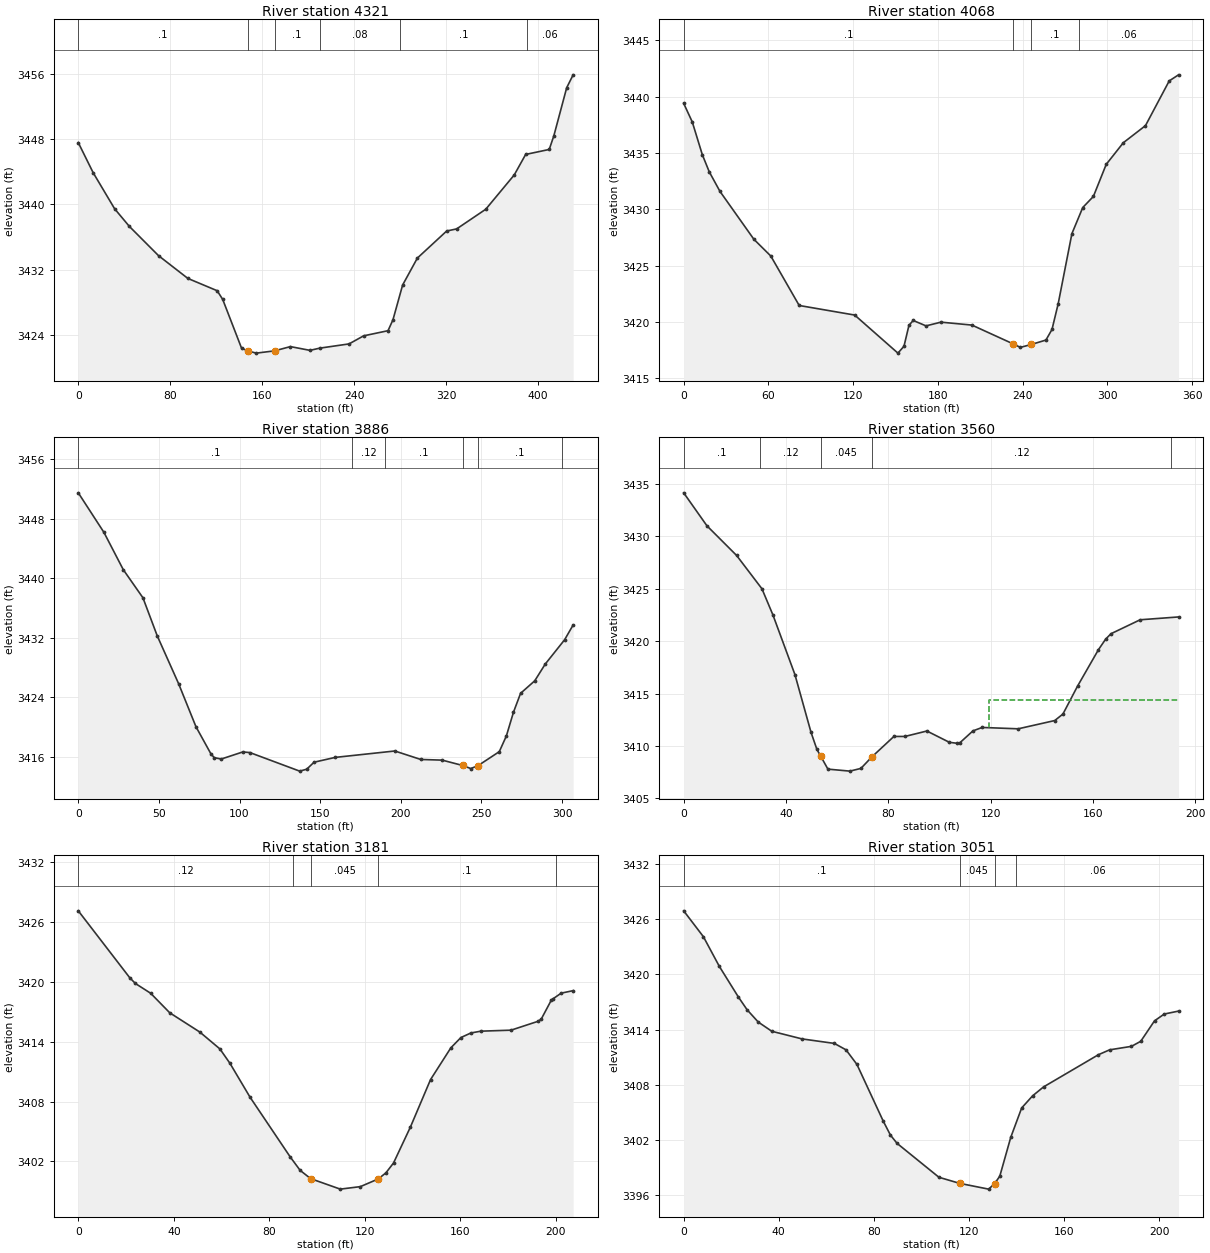
Type RM Length L Ch R = 1 ,4321    ,247.3,253.1,244.8
XS GIS Cut Line= 2
2349685.43094184589811.4052549342349830.02637483590216.746550703
#Sta/Elev= 30
       0 3447.57    12.9 3443.89    31.6 3439.46    44.4  3437.3    69.8 3433.71
    95.3 3430.92   120.8 3429.41   125.6 3428.35     142 3422.37   147.5 3422.03
   154.8 3421.76   170.73422.038   184.5 3422.56   201.5  3422.1     210 3422.37
   235.5 3422.89   248.2 3423.88   269.4 3424.51   273.7 3425.85   282.1 3430.11
   294.9 3433.41   320.4 3436.73   329.1 3436.99   354.4  3439.4   379.2 3443.61
   389.1 3446.12   409.6 3446.73   413.6 3448.39   424.8  3454.3   430.4 3455.88
#Mann= 6 ,-1,0
       0      .1       0   147.5    .045       0   170.7      .1       0
     210     .08       0     280      .1       0     390     .06       0
Bank Sta=147.5,170.7
XS Rating Curve= 0 ,0
Exp/Cntr(USF)=0,0
Exp/Cntr=0.3,0.1

Type RM Length L Ch R = 1 ,4068    ,181,181.9,180.5
XS GIS Cut Line= 3
2349576.53071019589915.5291270752349577.15030469589995.456818269
2349685.57934313590243.294620418
#Sta/Elev= 30
       0 3439.41     6.1 3437.75    13.2 3434.85    18.1 3433.33    25.7 3431.59
    49.7 3427.34    61.7 3425.85    81.8 3421.46   121.1 3420.61   151.7 3417.23
     156 3417.84   159.5 3419.69   162.5 3420.13   171.6 3419.65   182.2 3419.98
   204.1 3419.72   233.53418.039   238.4 3417.74   246.2    3418   256.5 3418.39
   260.8 3419.33   265.2 3421.62   274.9 3427.84   282.6 3430.16   290.1 3431.14
   299.2 3433.99   311.3 3435.91     327 3437.43   343.8  3441.4   350.4 3441.94
#Mann= 4 ,-1,0
       0      .1       0   233.5    .045       0   246.2      .1       0
  279.93     .06       0
Bank Sta=233.5,246.2
XS Rating Curve= 0 ,0
Exp/Cntr(USF)=0,0
Exp/Cntr=0.3,0.1

Type RM Length L Ch R = 1 ,3886    ,324.1,325.9,319.8
XS GIS Cut Line= 2
 2349387.3256424 590000.864785622349517.70839561590278.636738111
#Sta/Elev= 30
       0  3451.5    15.9 3446.18    27.9 3441.16    40.1 3437.37      49 3432.23
    62.2 3425.82      73 3420.01    82.2 3416.39    84.3 3415.85    88.7 3415.67
     102 3416.62   106.4 3416.54   137.3 3414.04   141.7  3414.3   146.2 3415.24
   159.4 3415.89   196.3 3416.75   212.4 3415.61   225.7 3415.52   238.4  3414.8
   243.4 3414.39   247.8 3414.76   261.1 3416.66   265.5 3418.78   269.9 3421.97
   274.3 3424.51   283.1  3426.2   289.6 3428.45   301.6 3431.72   306.9 3433.71
#Mann= 6 ,-1,0
       0      .1       0     170     .12       0     190      .1       0
   238.4    .045       0   247.8      .1       0     300     .06       0
Bank Sta=238.4,247.8
XS Rating Curve= 0 ,0
Exp/Cntr(USF)=0,0
Exp/Cntr=0.3,0.1

Type RM Length L Ch R = 1 ,3560    ,374.1,379.7,379
XS GIS Cut Line= 3
2349165.83232825590144.714376592 2349210.2761286590256.945841102
 2349268.0757623590301.215062796
#Sta/Elev= 30
       0 3434.16     9.1 3431.01    20.7 3428.18    30.6    3425    34.9  3422.5
    43.5 3416.81    49.8 3411.29    52.1 3409.66    53.6 3409.01    56.4 3407.78
      65 3407.59    69.3 3407.85    73.6 3408.95    82.2  3410.9    86.5  3410.9
    95.1 3411.42   103.9 3410.34   106.9 3410.25   108.1 3410.32   113.1 3411.43
   116.7 3411.76   130.8 3411.63   145.1 3412.42   148.3 3413.04     154  3415.7
   162.2 3419.19     165 3420.19   167.1 3420.71   178.5 3422.04   193.5 3422.31
#Mann= 5 ,-1,0
       0      .1       0      30     .12       0    53.6    .045       0
    73.6     .12       0  190.71     .06       0
#XS Ineff= 2 , 0
                          119.27         3414.37
Permanent Ineff=
       F       F
Bank Sta=53.6,73.6
XS Rating Curve= 0 ,0
Exp/Cntr(USF)=0,0
Exp/Cntr=0.3,0.1

Type RM Length L Ch R = 1 ,3181    ,134.4,129.9,126.6
XS GIS Cut Line= 2
2348838.55925968590284.7259528152348902.04999168590482.000727238
#Sta/Elev= 30
       0 3427.11    21.5 3420.42    23.9 3419.83    30.3 3418.85    38.3 3416.89
    50.9 3414.96    59.3 3413.27    63.5 3411.83    71.9 3408.44    88.7 3402.46
    92.9  3401.1    97.3 3400.27   109.7 3399.22   118.1 3399.47   125.6 3400.24
   128.8 3400.85     132 3401.84   139.1 3405.46   147.5  3410.2     156 3413.38
   160.2 3414.41   164.4 3414.87   168.6 3415.05   181.2 3415.15   192.4 3416.03
   193.8 3416.24     198 3418.13   198.7 3418.28   202.2 3418.86   207.2 3419.11
#Mann= 5 ,-1,0
       0     .12       0      90      .1       0    97.3    .045       0
   125.6      .1       0     200     .06       0
Bank Sta=97.3,125.6
XS Rating Curve= 0 ,0
Exp/Cntr(USF)=0,0
Exp/Cntr=0.3,0.1

Type RM Length L Ch R = 1 ,3051    ,166.8,168,169.6
XS GIS Cut Line= 2
2348696.66933626590346.0236076612348800.76121316590526.325608725
#Sta/Elev= 30
       0 3426.93     8.3 3424.11      15 3420.88      23 3417.55    26.7 3416.15
    31.4 3414.81    37.1 3413.81    49.8 3412.98    63.4 3412.49    68.3 3411.79
    72.9  3410.2    83.9 3404.06      87  3402.5    89.8  3401.6   107.4 3397.91
   116.1 3397.25   128.3 3396.62   130.8 3397.21     133 3398.03   137.6 3402.25
   142.2 3405.46   146.8 3406.78   151.4 3407.75   174.5 3411.26   179.2 3411.79
   188.4 3412.17   192.3 3412.72   198.1 3414.95   202.2 3415.69   208.2 3416.01
#Mann= 4 ,-1,0
       0      .1       0   116.1    .045       0   130.8      .1       0
     140     .06       0
Bank Sta=116.1,130.8
XS Rating Curve= 0 ,0
Exp/Cntr(USF)=0,0
Exp/Cntr=0.3,0.1

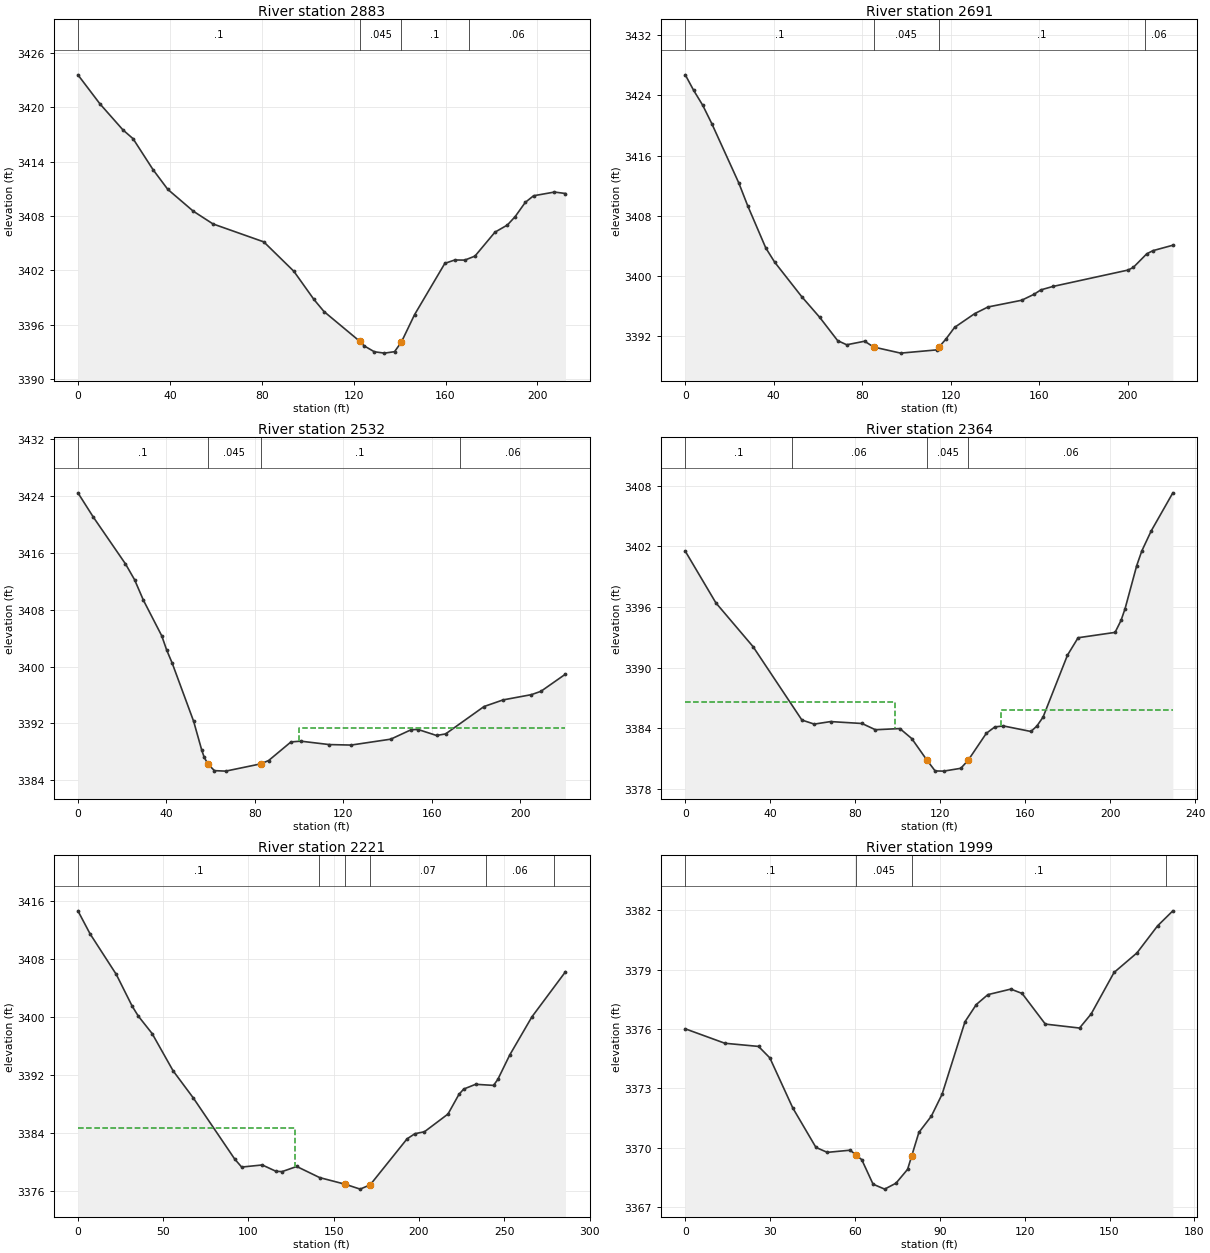
Type RM Length L Ch R = 1 ,2883    ,187.6,192.2,195.1
XS GIS Cut Line= 2
2348556.27731107590411.2870174642348642.44330449590605.160502673
#Sta/Elev= 30
       0 3423.57     9.6 3420.36    19.6 3417.49      24 3416.52    32.7  3413.1
    39.1 3410.93    50.2 3408.52    58.8 3407.11    80.9 3405.13      94 3401.88
   102.7 3398.78   107.1 3397.44   122.6 3394.17   124.6 3393.65     129    3393
   133.4 3392.85   137.8 3393.01   140.8 3394.08   146.5 3397.09   159.7 3402.76
     164 3403.13   168.4 3403.12   172.8 3403.56   181.5  3406.2   186.9 3406.99
   190.3 3407.92   194.7 3409.49   198.3 3410.22   207.4 3410.63   212.2 3410.47
#Mann= 4 ,-1,0
       0      .1       0   122.6    .045       0   140.8      .1       0
     170     .06       0
Bank Sta=122.6,140.8
XS Rating Curve= 0 ,0
Exp/Cntr(USF)=0,0
Exp/Cntr=0.3,0.1

Type RM Length L Ch R = 1 ,2691    ,172.8,158.6,145.4
XS GIS Cut Line= 3
2348408.55789126 590485.432371372348432.10248246590611.210055961
2348500.87747256590673.169506498
#Sta/Elev= 30
       0 3426.74     3.8 3424.67     7.9 3422.69      12 3420.25    24.2 3412.38
    28.2 3409.37    36.4 3403.75    40.4 3401.87    52.6  3397.3    60.8 3394.53
    68.9 3391.44      73 3390.89    81.1 3391.36    85.2 3390.59    97.4 3389.78
   113.7 3390.21  114.72 3390.58   117.8 3391.62   121.8  3393.2   130.9 3395.03
   136.9 3395.91   152.1  3396.8   157.7 3397.59   160.8 3398.18   166.2 3398.63
   200.2 3400.81   202.6 3401.16   208.7 3402.97   211.5 3403.39   220.5 3404.11
#Mann= 4 ,-1,0
       0      .1       0    85.2    .045       0  114.72      .1       0
  207.96     .06       0
Bank Sta=85.2,114.72
XS Rating Curve= 0 ,0
Exp/Cntr(USF)=0,0
Exp/Cntr=0.3,0.1

Type RM Length L Ch R = 1 ,2532    ,175.3,167.7,159.1
XS GIS Cut Line= 4
2348222.95096808590617.631896458 2348260.2900308590623.892941601
2348321.88180035590666.0699142312348422.49326864590704.931652955
#Sta/Elev= 30
       0 3424.48     6.9 3421.09    21.5 3414.47    25.6 3412.25    29.6 3409.36
    37.9 3404.34    40.1 3402.36    42.6 3400.51    52.3 3392.31      56 3388.22
    57.1 3387.22    58.8 3386.28    61.7 3385.36    66.8 3385.29    82.6 3386.31
    86.2 3386.78    96.3  3389.4   100.7 3389.51   113.6 3389.03   123.5 3388.96
   141.4 3389.79   150.7 3391.13   153.8 3391.15   162.1 3390.31   166.2 3390.53
   183.6 3394.39   192.2 3395.32     205 3396.06   209.3 3396.53   220.4 3398.95
#Mann= 4 ,-1,0
       0      .1       0    58.8    .045       0    82.6      .1       0
  172.51     .06       0
#XS Ineff= 2 , 0
                           99.84         3391.32
Permanent Ineff=
       F       F
Bank Sta=58.8,82.6
XS Rating Curve= 0 ,0
Exp/Cntr(USF)=0,0
Exp/Cntr=0.3,0.1

Type RM Length L Ch R = 1 ,2364    ,130.2,142.9,157.3
XS GIS Cut Line= 4
2348155.09508637590722.3845224482348202.85251547590796.468813068
 2348274.7254781590803.2843526272348322.22190711590853.588019718
#Sta/Elev= 30
       0 3401.51    14.4  3396.4    31.9 3392.07    54.9 3384.81    60.7 3384.41
    68.4 3384.66    83.2 3384.47    89.5 3383.85     101 3383.97   106.6 3382.98
   113.6 3380.89   117.6 3379.78   121.6 3379.76   129.7 3380.04   133.2 3380.85
   141.7  3383.5   145.7 3384.13   149.7 3384.23   162.7 3383.68   165.5 3384.22
   168.4  3385.1   179.9 3391.23   184.9 3392.95   202.3 3393.48   205.1 3394.66
     207 3395.82   212.5 3400.09   214.9 3401.54   219.3 3403.51   229.5 3407.28
#Mann= 4 ,-1,0
       0      .1       0      50     .06       0   113.6    .045       0
   133.2     .06       0
#XS Ineff= 2 , 0
           98.59 3386.62  148.59         3385.81
Permanent Ineff=
       F       F
Bank Sta=113.6,133.2
XS Rating Curve= 0 ,0
Exp/Cntr(USF)=0,0
Exp/Cntr=0.3,0.1

Type RM Length L Ch R = 1 ,2221    ,215.2,222.8,226.3
XS GIS Cut Line= 4
2348096.28226055590722.1174724232348114.25050121590852.232318551
2348148.94779351590910.4742020562348218.34237811590962.520140507
#Sta/Elev= 30
       0 3414.69     7.1 3411.52    22.5  3405.9    31.8 3401.52    35.4 3400.14
    43.5 3397.73    55.8 3392.58    67.7 3388.81    91.9 3380.39      96 3379.27
   108.1 3379.56   116.1 3378.69   119.7 3378.64   128.3 3379.35   141.8 3377.81
   156.8 3376.89   165.5 3376.22   171.4 3376.82     193 3383.17   197.6 3383.88
   203.2 3384.15     217  3386.6   223.4 3389.31   226.2 3390.05   233.2 3390.71
   243.7 3390.56   246.2 3391.38   253.2 3394.76   266.2 3400.03   285.9 3406.27
#Mann= 6 ,-1,0
       0      .1       0  141.35     .07       0   156.8    .045       0
   171.4     .07       0  239.14     .06       0  279.14      .1       0
#XS Ineff= 2 , 0
          127.27 3384.63
Permanent Ineff=
       F       F
Bank Sta=156.8,171.4
XS Rating Curve= 0 ,0
Exp/Cntr(USF)=0,0
Exp/Cntr=0.3,0.1

Type RM Length L Ch R = 1 ,1999    ,137.9,129.6,122.3
XS GIS Cut Line= 2
2347953.53575643590899.6568209832347981.87983322591069.721281692
#Sta/Elev= 30
       0 3376.01      14 3375.28    25.9 3375.12    29.9 3374.54      38 3372.01
    46.2 3370.01    50.2 3369.76    58.3 3369.87    60.43369.624    62.4 3369.39
    66.4 3368.15    70.5  3367.9    74.5  3368.2    78.6  3368.9    80.1  3369.6
    82.6 3370.77      87 3371.59    90.8  3372.7    98.9 3376.37   102.9 3377.24
     107 3377.74   115.1 3378.02   119.1  3377.8   127.3 3376.25   139.4 3376.05
   143.5 3376.76   151.6 3378.86   159.7 3379.85     167 3381.22   172.4 3381.98
#Mann= 4 ,-1,0
       0      .1       0    60.4    .045       0    80.1      .1       0
     170     .06       0
Bank Sta=60.4,80.1
XS Rating Curve= 0 ,0
Exp/Cntr(USF)=0,0
Exp/Cntr=0.3,0.1

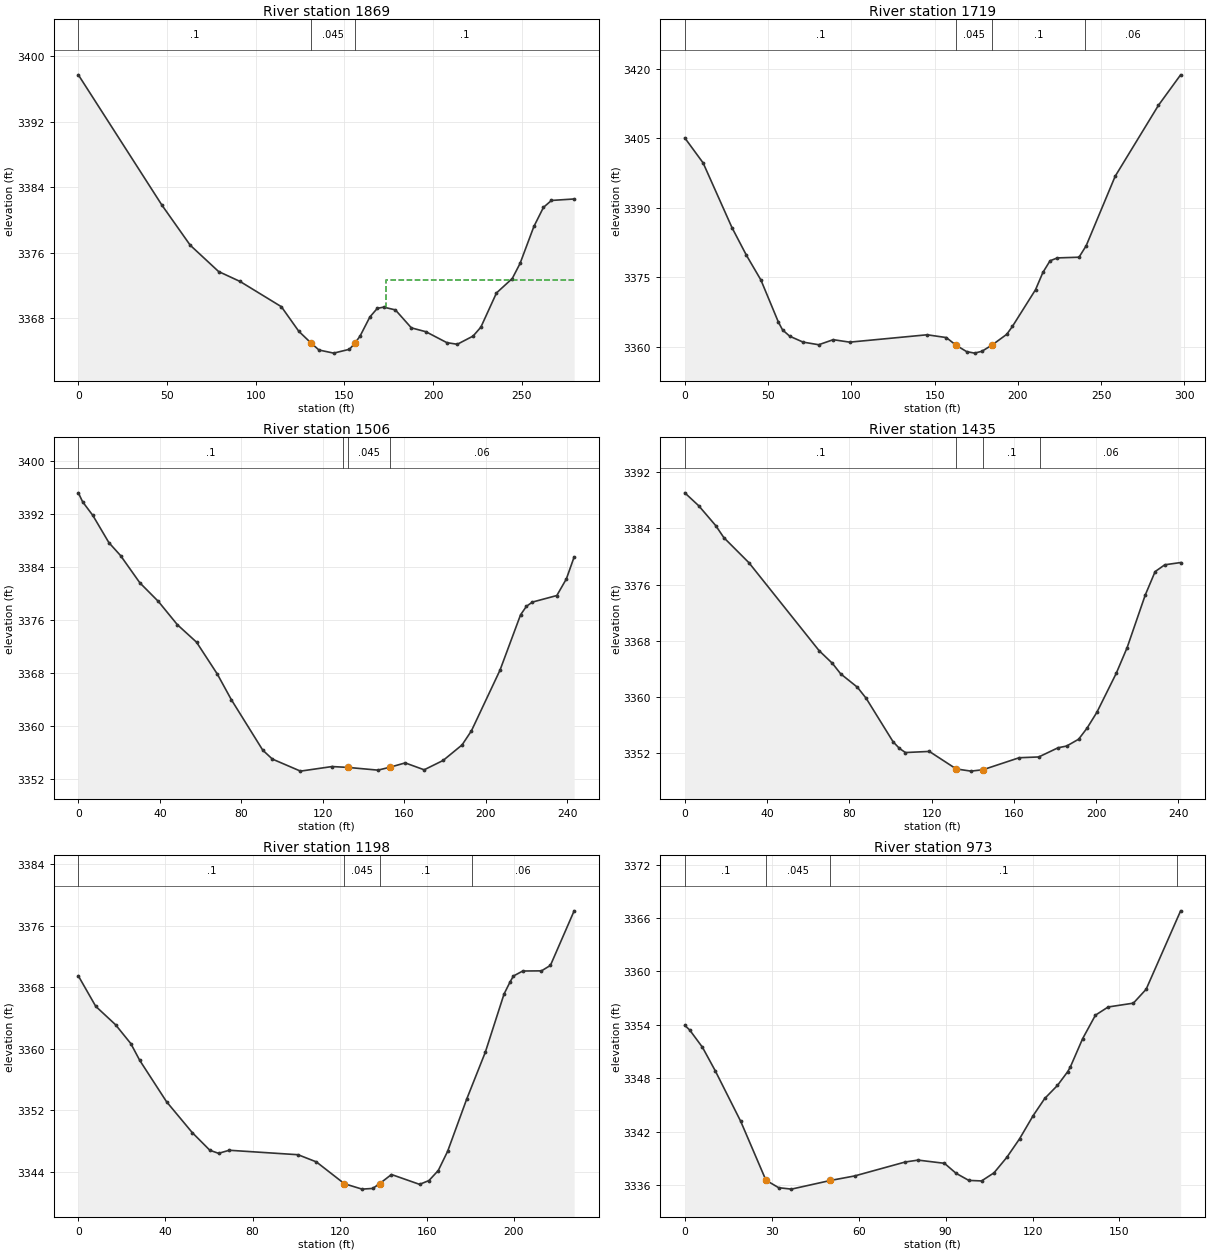
Type RM Length L Ch R = 1 ,1869    ,148.6,150.4,155.2
XS GIS Cut Line= 4
2347821.18230016590862.1458306372347816.22554412590958.802573475
2347863.31472653591024.4795910452347906.68634191591116.799172345
#Sta/Elev= 30
       0  3397.7    47.1 3381.82    63.1 3376.92    79.1 3373.71    91.2  3372.5
   114.5 3369.42   124.3 3366.43     131 3365.04   135.7 3364.14     144 3363.76
   152.9 3364.23   155.8 3364.94   158.8 3365.81   164.4 3368.17   168.6 3369.22
   172.2 3369.37   178.8 3369.03   187.8 3366.84     196 3366.37   207.8 3365.04
   213.7 3364.84   222.6 3365.84     227 3366.93   235.8  3371.1   244.7 3372.86
   249.1  3374.7   256.9 3379.21   262.3 3381.54   266.8 3382.38   279.6 3382.56
#Mann= 3 ,-1,0
       0      .1       0     131    .045       0   155.8      .1       0
#XS Ineff= 2 , 0
                          173.41         3372.66
Permanent Ineff=
       F       F
Bank Sta=131,155.8
XS Rating Curve= 0 ,0
Exp/Cntr(USF)=0,0
Exp/Cntr=0.3,0.1

Type RM Length L Ch R = 1 ,1719    ,205.5,212.4,200.6
XS GIS Cut Line= 2
2347660.60448467590935.0855564482347776.24831795591209.456219725
#Sta/Elev= 30
       0 3405.03      11 3399.63    28.3 3385.69      37  3379.7    45.7 3374.36
    56.2 3365.27    58.7 3363.59      63 3362.23      71 3360.96    80.4 3360.39
    89.1 3361.48      99 3360.95   145.5 3362.54     157 3361.94   162.9 3360.28
   169.2 3358.91     174 3358.58   178.4 3358.98   184.5 3360.33   193.3 3362.64
   196.7 3364.34   210.6 3372.28     215 3375.99   219.3 3378.51   223.7 3379.13
   236.7 3379.28     241 3381.76   258.4 3396.75   284.4 3412.07   297.7 3418.64
#Mann= 4 ,-1,0
       0      .1       0   162.9    .045       0   184.5      .1       0
     240     .06       0
Bank Sta=162.9,184.5
XS Rating Curve= 0 ,0
Exp/Cntr(USF)=0,0
Exp/Cntr=0.3,0.1

Type RM Length L Ch R = 1 ,1506    ,69.5,71.3,70.6
XS GIS Cut Line= 2
2347468.52584286 591043.374981032347592.94565723591252.493695584
#Sta/Elev= 30
       0 3395.14     2.1 3393.79     7.1 3391.74      15 3387.63    20.7 3385.69
    30.2 3381.57    39.3 3378.76    48.6 3375.26      58 3372.63    68.2 3367.82
    75.1 3363.95    90.5 3356.35    95.2 3355.01     109 3353.19   124.5 3353.88
   132.3 3353.75     147 3353.34   152.8 3353.77   160.4 3354.43   169.7 3353.39
     179  3354.8   188.3 3357.14   192.9 3359.27   206.9  3368.4     217 3376.75
   219.9 3378.04   222.8 3378.67   234.8 3379.66   239.5 3382.18   243.3 3385.48
#Mann= 4 ,-1,0
       0      .1       0     130     .06       0   132.3    .045       0
   152.8     .06       0
Bank Sta=132.3,152.8
XS Rating Curve= 0 ,0
Exp/Cntr(USF)=0,0
Exp/Cntr=0.3,0.1

Type RM Length L Ch R = 1 ,1435    ,234.8,237.1,238.2
XS GIS Cut Line= 3
2347467.21103384591058.4410501372347451.51424237591150.039193668
2347529.97956112591275.780321292
#Sta/Elev= 30
       0 3389.08     6.8 3387.23      15 3384.42      19 3382.69    31.2 3379.11
    65.3 3366.58    71.8 3364.76    75.8 3363.27    83.9 3361.37    88.2 3359.78
   101.3 3353.58   104.4 3352.63   107.3 3352.05   118.9 3352.21     132 3349.71
   139.2  3349.4     145  3349.6   162.6 3351.31   172.1 3351.42   181.5 3352.73
   185.7 3352.98   191.5 3353.95   195.6 3355.53   200.4  3357.8   209.8 3363.35
   215.1 3367.02   223.9 3374.51   228.7 3377.85   233.4 3378.82   241.1 3379.14
#Mann= 4 ,-1,0
       0      .1       0     132    .045       0     145      .1       0
  172.93     .06       0
Bank Sta=132,145
XS Rating Curve= 0 ,0
Exp/Cntr(USF)=0,0
Exp/Cntr=0.3,0.1

Type RM Length L Ch R = 1 ,1198    ,208.8,225.1,216.5
XS GIS Cut Line= 3
 2347289.2333613591177.2131317382347277.23040213591277.439557029
2347324.49872151 591395.03396054
#Sta/Elev= 30
       0 3369.46       8  3365.5    17.1 3363.11    24.1 3360.66    28.2 3358.48
    40.5 3353.11    52.3  3349.1    60.4  3346.8    64.4  3346.4    69.3  3346.8
   100.9 3346.22   109.3 3345.29   122.2 3342.45   130.3 3341.75   135.2 3341.84
   138.4 3342.47   143.8 3343.65   156.7 3342.37     161 3342.86   165.3 3344.17
   169.6 3346.67   178.3 3353.41   186.9 3359.54   195.5  3367.1   198.3 3368.69
   199.8 3369.44   204.1 3370.09   212.7 3370.11   216.8 3370.82   227.7 3377.91
#Mann= 4 ,-1,0
       0      .1       0   122.2    .045       0   138.4      .1       0
  180.94     .06       0
Bank Sta=122.2,138.4
XS Rating Curve= 0 ,0
Exp/Cntr(USF)=0,0
Exp/Cntr=0.3,0.1

Type RM Length L Ch R = 1 ,973     ,218.4,219.5,217.4
XS GIS Cut Line= 2
2347075.58273983591303.5585546512347144.74228718591460.017858503
#Sta/Elev= 30
       0 3353.95     1.7 3353.42     6.1 3351.48    10.5 3348.85    19.3 3343.16
      28 3336.55    32.4 3335.71    36.8 3335.55    50.2 3336.52    58.6 3337.03
    76.1  3338.6    80.5 3338.81    89.6 3338.45    93.6 3337.33      98 3336.53
   102.4 3336.47   106.7 3337.38   111.1 3339.11   115.5 3341.19   120.2  3343.8
   124.2 3345.73   128.6  3347.2   132.1 3348.73     133 3349.24   137.3 3352.46
   141.7 3355.09   146.1 3356.01   154.8 3356.44   159.2    3358   171.1 3366.81
#Mann= 4 ,-1,0
       0      .1       0      28    .045       0    50.2      .1       0
     170     .06       0
Bank Sta=28,50.2
XS Rating Curve= 0 ,0
Exp/Cntr(USF)=0,0
Exp/Cntr=0.3,0.1

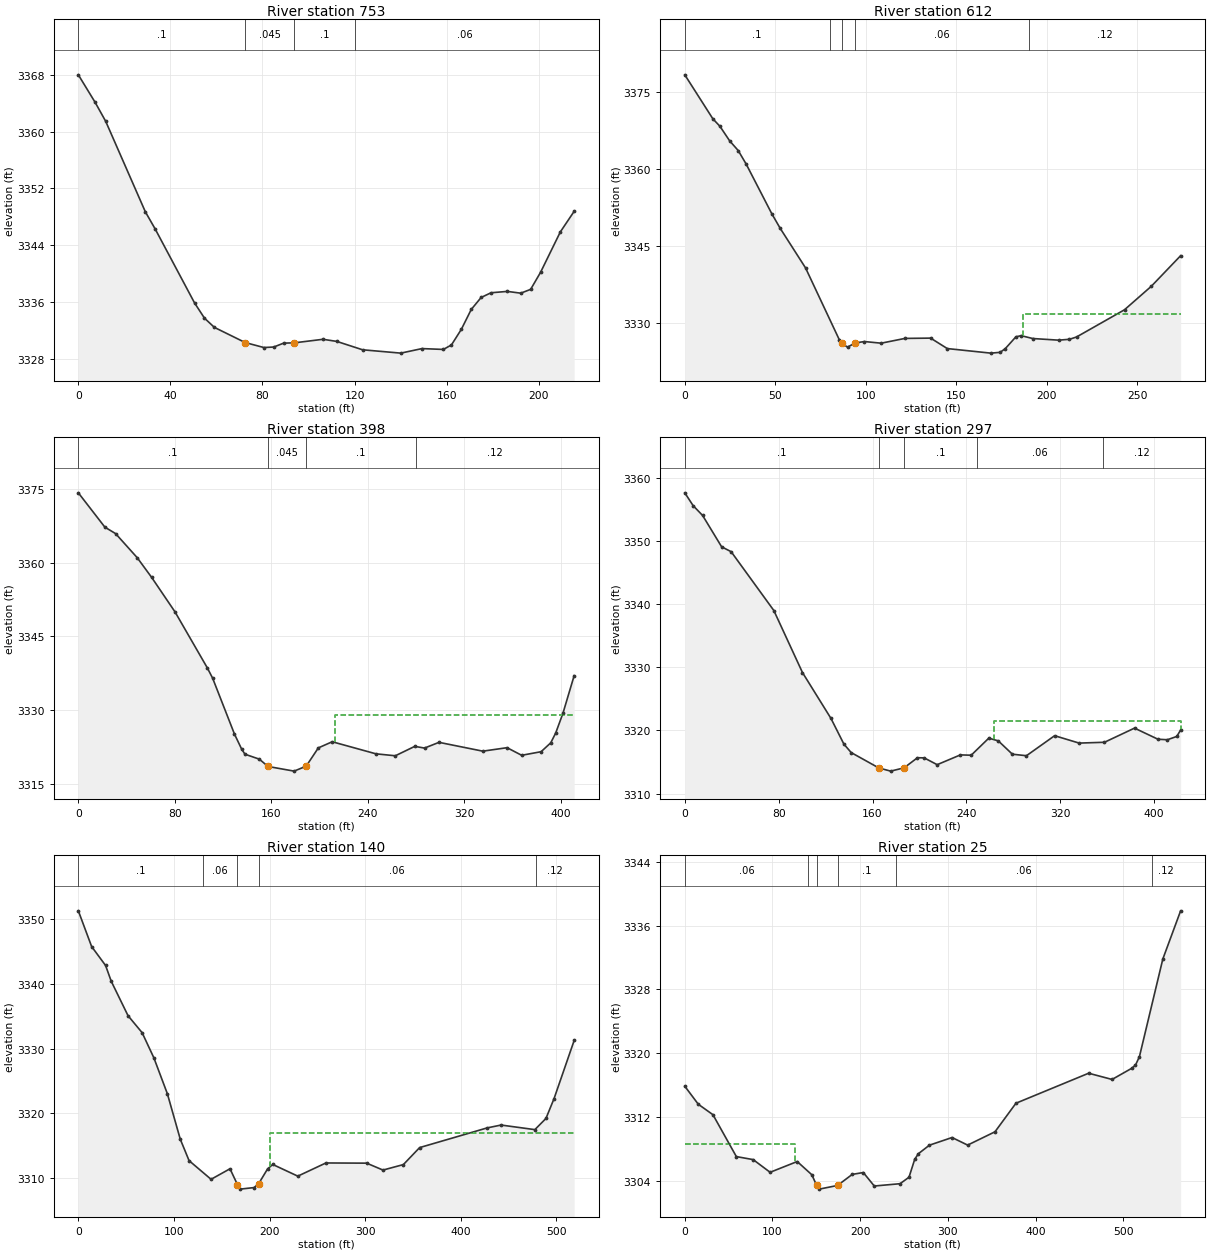
Type RM Length L Ch R = 1 ,753     ,142.6,141.3,139.5
XS GIS Cut Line= 2
2346865.83657162591342.1064990782346944.06622355591542.782562715
#Sta/Elev= 30
       0 3367.99     7.3 3364.11    11.9 3361.43    29.1 3348.69    33.4 3346.25
    50.5 3335.83    54.8 3333.69    59.1 3332.39    72.5 3330.25    80.6 3329.55
    84.9 3329.62    89.2 3330.17    93.8 3330.21   106.3 3330.71   112.3 3330.41
   123.5 3329.23   140.1 3328.76   149.3  3329.4   158.6 3329.28   162.1 3329.92
   166.4 3332.12   170.7 3334.92     175 3336.61   179.3 3337.27   186.4 3337.46
   192.2 3337.21   196.5 3337.75   200.8 3340.15   209.4 3345.85   215.4 3348.75
#Mann= 4 ,-1,0
       0      .1       0    72.5    .045       0    93.8      .1       0
     120     .06       0
Bank Sta=72.5,93.8
XS Rating Curve= 0 ,0
Exp/Cntr(USF)=0,0
Exp/Cntr=0.3,0.1

Type RM Length L Ch R = 1 ,612     ,211.4,213.6,212.9
XS GIS Cut Line= 3
2346718.89586955591387.8280552792346820.40757165591559.041183629
2346888.26810065591590.562351922
#Sta/Elev= 30
       0 3378.43    15.5 3369.85    19.4 3368.39    24.8 3365.54    29.5 3363.66
    33.9 3361.02    48.1  3351.3    52.7 3348.48    66.7 3340.76    85.3 3326.78
 86.79723326.049    89.9  3325.394.096963326.113    99.2 3326.39   108.5 3326.07
   121.6    3327   135.8 3327.06     145 3325.02     169 3324.13   174.2 3324.28
   177.1 3325.03   182.9 3327.31   185.8 3327.54   192.2 3326.98   206.5 3326.66
   212.5 3326.83   216.4 3327.28   242.9 3332.59   257.7 3337.17   273.9 3343.14
#Mann= 5 ,-1,0
       0      .1       0      80     .06       0 86.7972    .045       0
94.09696     .06       0     190     .12       0
#XS Ineff= 2 , 0
                          186.59         3331.86
Permanent Ineff=
       F       F
Bank Sta=86.7972,94.09696
XS Rating Curve= 0 ,0
Exp/Cntr(USF)=0,0
Exp/Cntr=0.3,0.1

Type RM Length L Ch R = 1 ,398     ,109.6,101.7,97.3
XS GIS Cut Line= 4
 2346538.4211509591449.462091569 2346601.2798888591576.077052773
2346645.33618771591640.7411186672346835.43424189591662.230463922
#Sta/Elev= 30
       0 3374.29      22 3367.29    30.9 3365.97    48.8 3361.06    60.8 3357.03
    80.1 3350.02   106.9 3338.59   111.3 3336.49   129.4 3325.09   135.4    3322
   138.1 3320.99     150 3319.98   157.2 3318.49   178.8 3317.54188.83743318.554
   198.9 3322.28   210.4 3323.53   246.6 3321.07   262.7 3320.67   278.8 3322.59
   286.9 3322.24   298.9 3323.41   335.2 3321.61   355.3 3322.32   367.4 3320.77
   383.5  3321.5   391.5 3323.31   395.6 3325.31   401.6 3329.33   410.9 3337.01
#Mann= 4 ,-1,0
       0      .1       0   157.2    .045       0188.8374      .1       0
  279.61     .12       0
#XS Ineff= 1 ,-1
  212.39   410.2 3328.95
Permanent Ineff=
       F
Bank Sta=157.2,188.8374
XS Rating Curve= 0 ,0
Exp/Cntr(USF)=0,0
Exp/Cntr=0.3,0.1

Type RM Length L Ch R = 1 ,297     ,153.5,156.8,156
XS GIS Cut Line= 4
2346486.52449299 591518.184496482346506.92266601591645.673077832
2346609.76345496591721.3163027682346775.49861072591714.516911763
#Sta/Elev= 30
       0 3357.63     7.1  3355.6    15.2 3354.04    31.4 3349.08    39.5 3348.31
    75.9 3338.99   100.3 3329.17   124.6  3321.9   135.6 3317.84   141.8  3316.5
   165.4 3314.06   175.5 3313.56   186.9 3314.08   198.3 3315.68     204 3315.66
   215.1 3314.58   234.9 3316.13   244.1 3316.08   259.1 3318.78   267.2 3318.35
   279.2 3316.24   291.2    3316   315.2 3319.17   336.1    3318   357.7 3318.13
   383.3 3320.37   403.3 3318.61   411.3 3318.53   419.3 3319.05   422.6 3320.07
#Mann= 5 ,-1,0
       0      .1       0   165.4    .045       0   186.9      .1       0
  249.11     .06       0  356.77     .12       0
#XS Ineff= 2 , 0
                          263.38         3321.57
Permanent Ineff=
       F       F
Bank Sta=165.4,186.9
XS Rating Curve= 0 ,0
Exp/Cntr(USF)=0,0
Exp/Cntr=0.3,0.1

Type RM Length L Ch R = 1 ,140     ,114.8,114.8,114.8
XS GIS Cut Line= 4
2346382.06571472591640.3979371142346461.02677672 591779.96105019
2346524.73904843 591824.705239352346787.89824791591728.200880646
#Sta/Elev= 30
       0 3351.33    13.9  3345.8    28.5 3342.87    34.4 3340.43      52 3335.09
    66.7 3332.47      79 3328.57    93.1 3323.02   106.6 3315.98   115.8 3312.66
   138.8 3309.77   158.6  3311.4   166.4 3308.95   169.2 3308.25   183.8 3308.49
   188.6  3309.1   197.9 3311.38   203.3 3312.07   229.5 3310.26   258.9  3312.3
   301.5 3312.27   318.6  3311.2   339.9 3312.05   356.9 3314.68   427.6 3317.73
   442.1 3318.17   477.4 3317.46     489 3319.19   497.5 3322.27   518.5 3331.26
#Mann= 5 ,-1,0
       0      .1       0     130     .06       0   166.4    .045       0
   188.6     .06       0  478.21     .12       0
#XS Ineff= 2 , 0
                          200.33         3316.98
Permanent Ineff=
       F       F
Bank Sta=166.4,188.6
XS Rating Curve= 0 ,0
Exp/Cntr(USF)=0,0
Exp/Cntr=0.3,0.1

Type RM Length L Ch R = 1 ,25      ,,,
XS GIS Cut Line= 4
2346277.47154406591858.6302402392346402.27282542591896.265794045
2346557.39589867 591847.878780372346802.44394253591728.351526246
#Sta/Elev= 30
       0 3315.86    15.4  3313.6    32.1 3312.29    58.8 3307.04      78 3306.66
    97.3 3305.07   128.2 3306.42   144.9 3304.76   150.3 3303.44   153.3 3302.96
   174.2 3303.42     191 3304.81   203.6 3305.04   216.1 3303.35   245.5 3303.64
   255.7 3304.45   262.2 3306.69   266.4  3307.4     279 3308.47   304.8 3309.43
   322.6 3308.48   353.8 3310.15   377.7 3313.73   460.6 3317.49   487.3 3316.71
   509.6  3318.1     514  3318.5   518.5 3319.56   545.2 3331.81   565.5 3337.85
#Mann= 6 ,-1,0
       0     .06       0  140.35      .1       0   150.3    .045       0
   174.2      .1       0  240.35     .06       0  532.85     .12       0
#XS Ineff= 2 , 0
          126.08  3308.6
Permanent Ineff=
       F       F
Bank Sta=150.3,174.2
XS Rating Curve= 0 ,0
Exp/Cntr(USF)=0,0
Exp/Cntr=0.3,0.1
LCMann Table=0

Chan Stop Cuts=-1
Use User Specified Reach Order=0
Composite Channel Slope=5